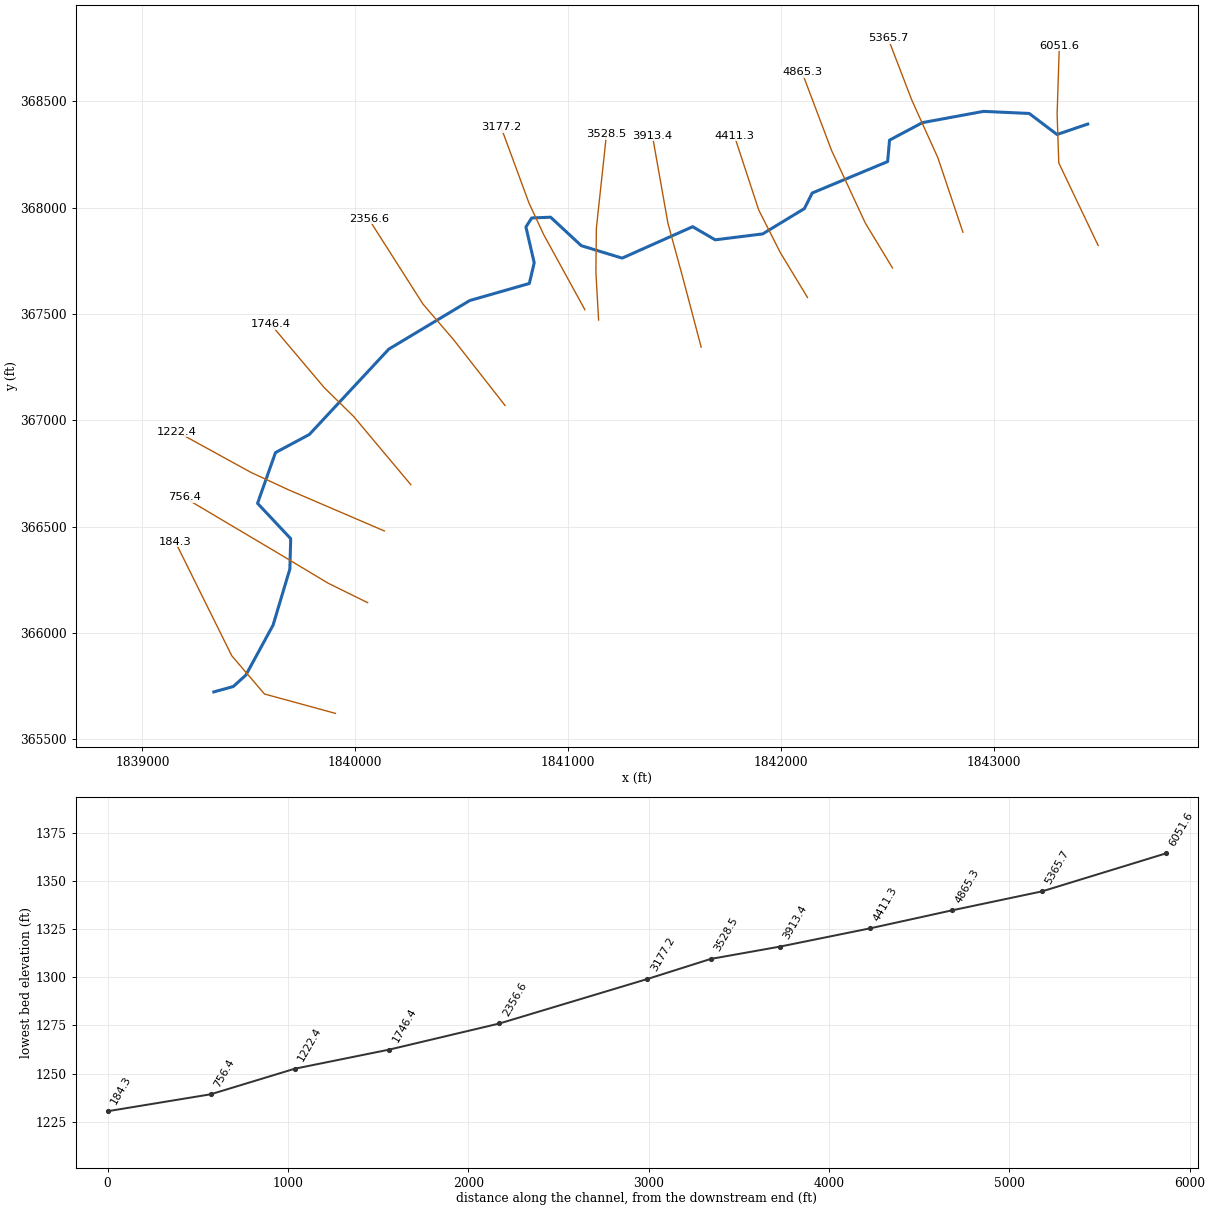
--- BoothsCkT.prj (project) ---

Proj Title=BoothsCkT
Current Plan=p01
Default Exp/Contr=0,0
English Units
Geom File=g01
Flow File=f01
Plan File=p01
BEGIN DESCRIPTION:
END DESCRIPTION:
DSS Export Rating Curves= 0
DSS Export Rating Curve Sorted= 0
DSS Export Volume Flow Curves= 0
DXF OffsetX= 0
DXF OffsetY= 0
DXF ScaleX= 0
DXF ScaleY= 0

--- BoothsCkT.p01 (plan) ---

Plan Title=Floodplain
Program Version=4.00
Geom File=g01
Flow File=f01
K Sum by GR=0
Std Step Tol=0.01
Critical Tol=0.01
Num of Std Step Trials=20
Max Error Tol=0.3
Flow Tol Ratio=0.001
Split Flow NTrial=30
Split Flow Tol=0.02
Split Flow Ratio=0.02
Log Output Level=0
Friction Slope Method=1
Unsteady Friction Slope Method=2
Unsteady Bridges Friction Slope Method=1
Global Log Level=0
CheckData=False
Run HTab=0
Run UNet=0
Run PostProcess=0
UNET Theta=0
UNET Theta Warmup=0
UNET ZTol=0
UNET ZSATol=0
UNET MxIter=0
UNET MaxInSteps=0
UNET DtIC=0
UNET DtMin=0
UNET MaxCRTS=0
UNET WFStab=0
UNET SFStab=0
UNET WFX=0
UNET SFX=0
UNET DSS MLevel=0
UNET DZMax Abort=0
UNET Convert EG Bridges=0
UNET Use Existing IB Tables=0
UNET Froude Limit=0
UNET Froude Power=0
Write IC File=0
Echo Input=False
Echo Output=False
Write Detailed=0

--- BoothsCkT.f01 (steady flow) ---

Flow Title=NFF Regression Equation
Program Version=4.10
Number of Profiles= 1
Profile Names=P100yr
River Rch & RM=BoothsCkT,Main            ,6051.6
     783
River Rch & RM=BoothsCkT,Main            ,3177.2
     878
River Rch & RM=BoothsCkT,Main            ,1746.4
     919
River Rch & RM=BoothsCkT,Main            ,184.3
     943
Boundary for River Rch & Prof#=BoothsCkT,Main            , 1
Up Type= 0
Dn Type= 3
Dn Slope=0.01529
DSS Import GetInterval= 0
DSS Import GetPeak= 0
DSS Import FillOption= 0

--- BoothsCkT.g01 (geometry) ---

Geom Title=USGS 10m DEM
Program Version=4.10

River Reach=BoothsCkT       ,Main
Reach XY= 30
     1843441.059      368393.654     1843297.048      368344.566
     1843166.449      368443.524     1842951.345       368453.29
     1842664.674      368400.349      1842510.16      368317.993
     1842501.263       368217.19     1842146.705      368069.273
     1842110.117      367996.096     1841914.226      367877.071
     1841691.135      367849.206     1841585.319      367910.969
      1841253.95      367763.236     1841061.936      367821.765
     1840917.839      367955.619     1840829.092      367952.149
     1840801.828      367909.793     1840840.776      367741.341
     1840817.894       367643.97     1840537.709      367563.639
     1840157.524      367335.109     1839784.302      366933.844
     1839625.198      366848.645     1839540.972      366610.086
     1839696.765      366443.873      1839692.87      366301.712
        1839614.      366037.545     1839486.054      365802.297
     1839427.145      365748.743     1839335.642      365723.246

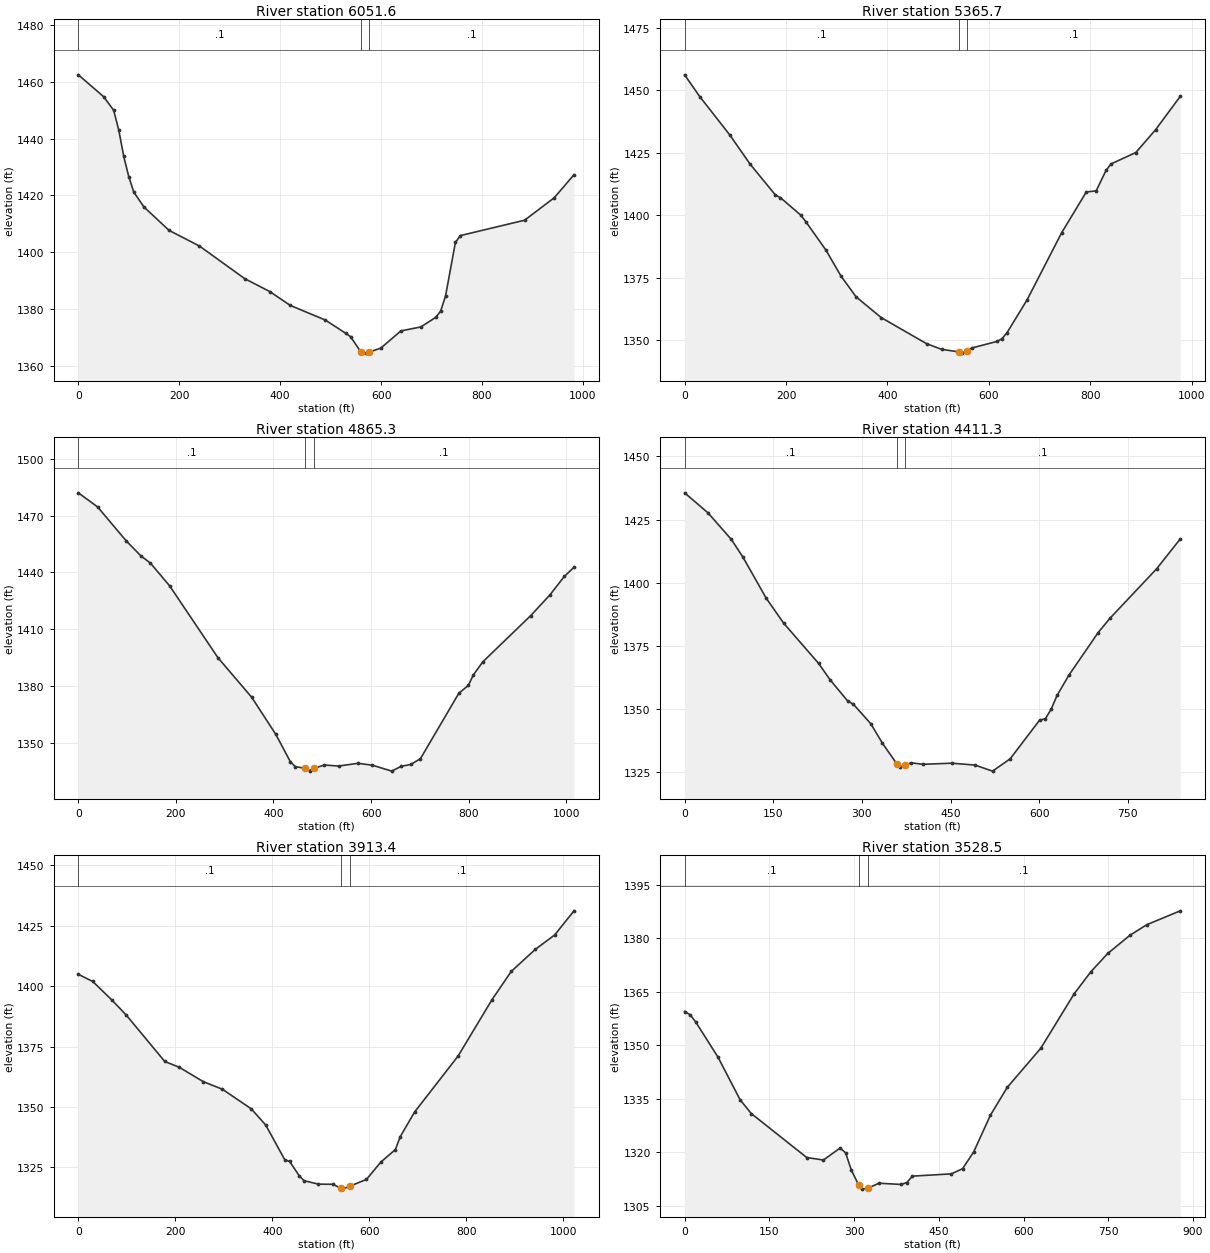
Type RM Length L Ch R = 1 ,6051.6  ,676.4,685.8,693.8
XS GIS Cut Line= 4
     1843490.204      367822.842     1843305.308      368210.863
     1843297.496      368440.029     1843307.912      368762.946
#Sta/Elev= 30
       0 1462.49      50 1454.82      70 1450.02      80 1443.15      90 1433.77
     100 1426.58     110 1421.15     130 1415.96   179.9 1407.69   239.9 1402.21
   329.9 1390.69   379.8 1386.12   419.8  1381.3   489.6 1376.12   529.5  1371.5
   539.5 1370.27   559.4 1365.01   569.4 1364.48  575.08 1364.78   599.3 1366.24
   639.2 1372.31   678.7  1373.7   708.1 1377.06   717.9 1379.27   727.6 1384.56
   747.2 1403.46     757 1405.87   884.3 1411.29     943 1419.19   982.2 1427.31
#Mann= 3 , 0 , 0
       0      .1       0   559.4    .045       0  575.08      .1       0
Bank Sta=559.4,575.08
XS Rating Curve= 0 ,0
Exp/Cntr=0.3,0.1

Type RM Length L Ch R = 1 ,5365.7  ,499.7,500.4,500.2
XS GIS Cut Line= 4
     1842854.787      367885.342       1842737.6        368234.3
     1842615.204      368505.134     1842503.225        368796.8
#Sta/Elev= 30
       0 1456.21    29.8 1447.51    89.5 1432.02   129.3  1420.4   179.1 1408.08
     189 1407.02   228.8 1400.08   238.8 1397.46   278.6 1386.06   308.4 1375.62
   338.3 1367.27   387.9 1358.96   477.1 1348.55   506.8 1346.27   541.9 1345.21
   546.4 1344.75   556.3 1345.46   566.2  1346.8   615.8 1349.41   625.7 1350.49
   635.6 1352.83   675.1 1365.94   743.4 1392.87   792.2 1409.27   811.8 1409.76
   831.3 1417.97     841 1420.53   889.9 1425.08   928.9 1434.21   977.7 1447.61
#Mann= 3 , 0 , 0
       0      .1       0   541.9    .045       0   556.3      .1       0
Bank Sta=541.9,556.3
XS Rating Curve= 0 ,0
Exp/Cntr=0.3,0.1

Type RM Length L Ch R = 1 ,4865.3  ,452.7,454,454.7
XS GIS Cut Line= 4
     1842524.058      367716.939     1842396.454      367927.877
     1842238.041      368268.849     1842099.152      368636.904
#Sta/Elev= 30
       0 1482.13    39.4  1474.7    98.6 1456.58   128.2 1448.78   147.9  1444.9
   187.4 1432.81   286.1  1394.9   355.4 1373.91   404.8 1354.28   434.5 1339.86
   444.4 1337.25   464.2 1336.37   474.1 1335.12     484 1336.37   503.8 1338.09
   533.5 1337.54     573 1338.99   602.7 1337.99   642.2 1334.85   661.8  1337.4
   681.5 1338.39   701.2 1341.45   779.9 1376.08   799.5 1380.25   809.4 1385.69
     829 1392.69   927.4 1417.21   966.7 1428.15   996.2 1437.93  1015.9 1442.73
#Mann= 3 , 0 , 0
       0      .1       0   464.2    .045       0     484      .1       0
#XS Ineff= 2 , 0
                          573.01         1338.94
Permanent Ineff=
       F       F
Bank Sta=464.2,484
XS Rating Curve= 0 ,0
Exp/Cntr=0.3,0.1

Type RM Length L Ch R = 1 ,4411.3  ,502.9,497.9,492.3
XS GIS Cut Line= 4
     1842124.753       367578.05     1841997.149      367788.988
     1841895.586      367989.509     1841781.003      368338.467
#Sta/Elev= 30
       0 1435.62    39.4 1427.72    78.9 1417.22    98.6  1410.2   138.1  1393.9
   167.6 1384.03   226.8 1368.09   246.5 1361.51   275.8 1353.28   285.6 1351.94
   314.9 1344.28   334.5  1336.6  359.62 1328.16   363.8 1327.18   373.6 1327.99
   383.4  1328.8   402.9  1328.2   451.8 1328.64   491.2  1327.9   520.9  1325.5
   550.7 1330.35   600.4 1345.63   610.3 1346.24   620.2 1350.04   630.1 1355.46
     650 1363.43   699.6 1380.32   719.5 1385.96   798.9 1405.66   838.6  1417.4
#Mann= 3 , 0 , 0
       0      .1       0  359.62    .045       0   373.6      .1       0
Bank Sta=359.62,373.6
XS Rating Curve= 0 ,0
Exp/Cntr=0.3,0.1

Type RM Length L Ch R = 1 ,3913.4  ,390.1,384.8,378.3
XS GIS Cut Line= 4
     1841625.187      367344.543     1841539.249      367670.064
     1841468.937      367927.877      1841396.02      368339.335
#Sta/Elev= 30
       0 1404.85    29.7 1401.89    69.3 1394.21      99 1387.96   178.2 1368.81
     208 1366.42   257.5 1360.48   297.1 1357.32   356.5 1349.23   386.2 1342.56
   425.8 1328.11   435.6 1327.47   455.4 1321.55   465.3 1319.52     495 1318.09
   524.7 1318.03   541.8 1316.34   544.5 1316.03  560.66 1317.33     594 1320.06
   623.8 1327.26   653.6 1332.39   663.6 1337.73   693.4 1347.97     783  1371.1
   852.6 1394.32   892.4 1406.04   942.2 1415.19     982 1421.13  1021.8  1431.1
#Mann= 3 , 0 , 0
       0      .1       0   541.8    .045       0  560.66      .1       0
Bank Sta=541.8,560.66
XS Rating Curve= 0 ,0
Exp/Cntr=0.3,0.1

Type RM Length L Ch R = 1 ,3528.5  ,341.4,351.3,360.7
XS GIS Cut Line= 4
      1841143.25      367471.974     1841130.547      367697.668
     1841132.833      367904.266      1841180.46       368346.54
#Sta/Elev= 30
       0 1359.39     9.8 1358.49    19.7 1356.45      59 1346.62    98.3 1334.63
   117.9  1330.8   216.2 1318.46   245.7 1317.76   275.2 1321.12   285.1 1319.76
   294.9    1315   308.4 1310.65   314.6  1309.6   324.4 1309.87   344.1 1311.26
   383.5 1310.91   393.3 1311.45   403.2 1313.24   472.2 1313.88     492 1315.33
   511.7 1320.02   541.4 1330.34     571  1338.1   630.4 1349.07   689.7 1364.39
   719.3 1370.57     749 1375.66   788.5 1380.79   818.2 1383.73   877.5 1387.62
#Mann= 3 , 0 , 0
       0      .1       0   308.4    .045       0   324.4      .1       0
Bank Sta=308.4,324.4
XS Rating Curve= 0 ,0
Exp/Cntr=0.3,0.1

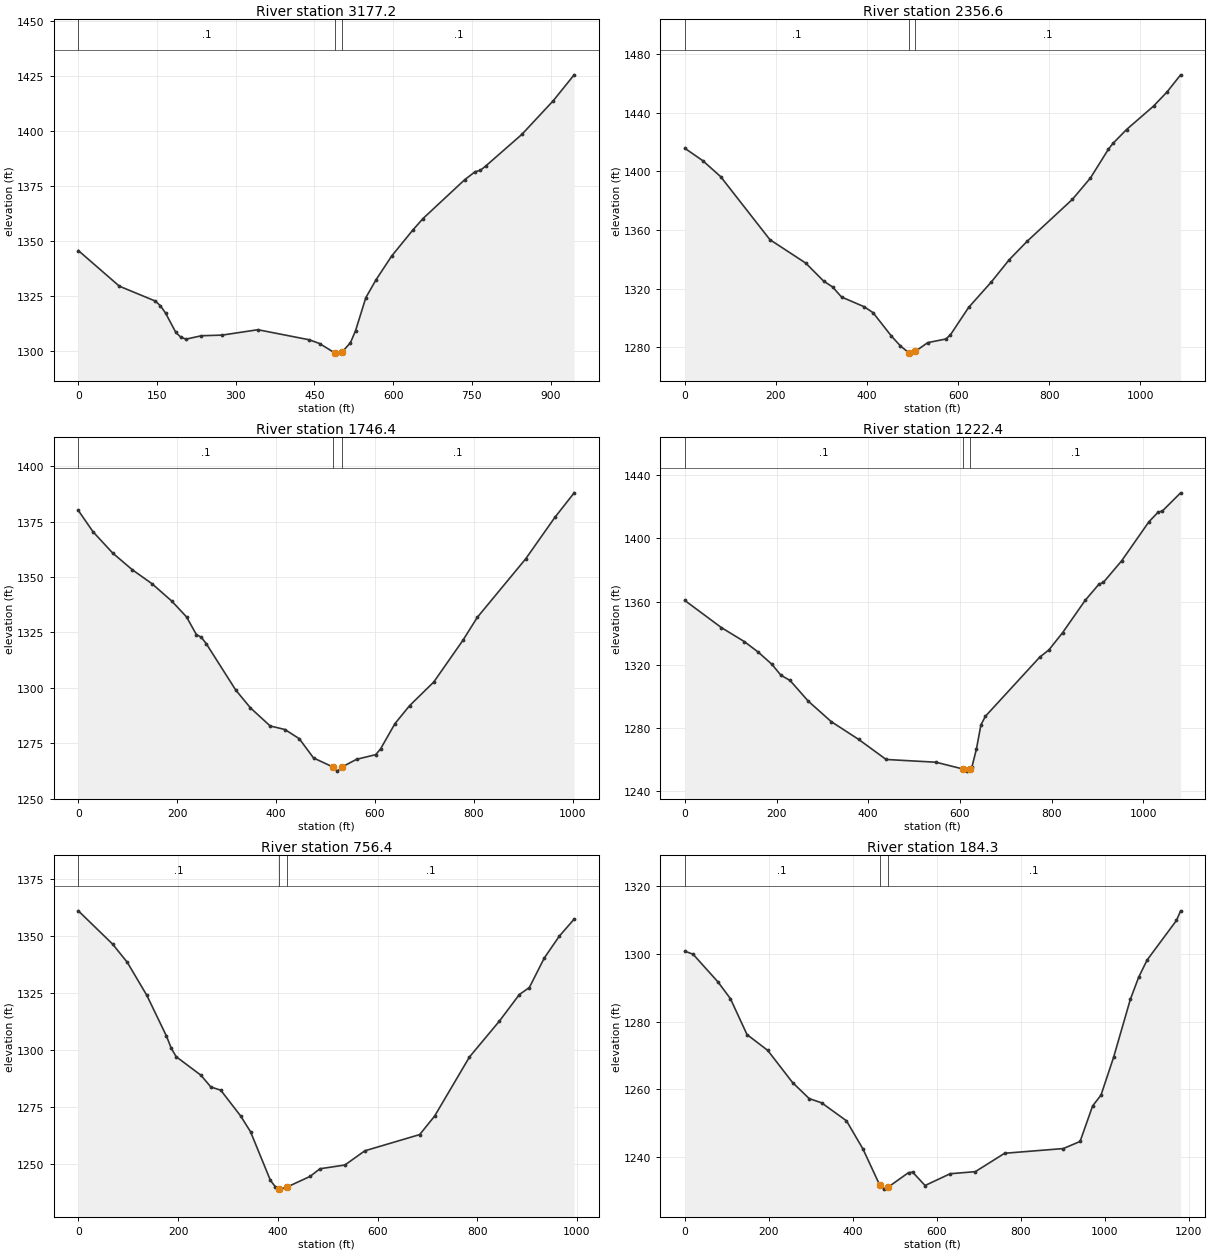
Type RM Length L Ch R = 1 ,3177.2  ,813.7,820.5,826.6
XS GIS Cut Line= 4
     1841078.746      367520.759     1840886.037      367872.321
     1840815.725      368023.363     1840685.517      368377.529
#Sta/Elev= 30
       0 1345.75    78.2 1329.56   146.7 1322.81   156.4 1320.67   166.2 1317.37
   185.8 1308.57   195.6 1306.34   205.4 1305.52   234.7 1307.06   273.8 1307.34
   342.2 1309.79   440.1 1305.22   459.7 1303.53   488.4 1299.29   498.9 1299.16
   503.4 1299.89   518.5 1303.84   528.3 1309.36   547.9 1324.36   567.5 1332.55
   597.3 1343.31     637 1354.93   656.9  1360.3   736.3 1377.92   756.2 1381.55
   766.1 1382.18     776 1384.05   845.6 1398.58   905.1  1413.8   944.9 1425.55
#Mann= 3 , 0 , 0
       0      .1       0   488.4    .045       0   503.4      .1       0
Bank Sta=488.4,503.4
XS Rating Curve= 0 ,0
Exp/Cntr=0.3,0.1

Type RM Length L Ch R = 1 ,2356.6  ,608.2,610.2,612
XS GIS Cut Line= 4
     1840703.746      367070.238     1840461.558      367380.134
     1840318.329        367546.8     1840063.121      367947.842
#Sta/Elev= 30
       0 1415.66    39.3 1407.25    78.7 1396.32   186.8 1353.37   265.5 1337.39
   304.8 1325.12   324.5 1321.11   344.1 1314.26   393.3  1307.7   413.3  1303.6
   453.2 1287.78   473.2 1280.97   491.2 1276.42   493.2 1276.02   506.2 1277.27
   533.2 1283.16   573.1 1285.66   583.1 1288.49     623 1307.15   672.5 1324.39
   712.1 1339.66   751.7 1352.33   850.7 1380.79   890.4 1395.38     930 1415.07
   939.9 1418.98   969.6  1428.4    1029  1444.4  1058.7 1454.09  1088.4 1465.71
#Mann= 3 , 0 , 0
       0      .1       0   491.2    .045       0   506.2      .1       0
Bank Sta=491.2,506.2
XS Rating Curve= 0 ,0
Exp/Cntr=0.3,0.1

Type RM Length L Ch R = 1 ,1746.4  ,516.2,524,532
XS GIS Cut Line= 4
     1840261.037      366697.842     1839992.808      367018.154
     1839854.787      367153.571     1839602.183       367453.05
#Sta/Elev= 30
       0 1380.06    29.8 1370.42    69.6 1360.82   109.4 1353.26   149.2 1346.98
     189 1339.16   218.8 1332.05   238.7 1324.09   248.7 1322.84   258.6 1320.01
   318.3 1299.06   348.2 1290.97     388 1282.83   417.8 1281.23   446.8  1277.1
   475.8 1268.38   514.5 1264.37   524.1 1262.45   533.8 1264.37   562.8 1267.79
   601.5 1269.88   611.2 1272.44   640.5 1283.91   669.9 1291.96   718.9 1302.65
   777.7 1321.42     807 1331.83     905 1358.27   963.8 1376.91  1002.9 1388.01
#Mann= 3 , 0 , 0
       0      .1       0   514.5    .045       0   533.8      .1       0
Bank Sta=514.5,533.8
XS Rating Curve= 0 ,0
Exp/Cntr=0.3,0.1

Type RM Length L Ch R = 1 ,1222.4  ,467.6,465.9,464.2
XS GIS Cut Line= 4
     1840136.623       366480.22     1839687.405      366673.363
     1839509.453      366755.828     1839162.231        366946.8
#Sta/Elev= 30
       0 1360.71    79.8  1343.5   129.7 1334.65   159.7 1328.06   189.6 1320.34
   209.6  1313.3   229.5 1309.99   269.4 1296.84   319.3  1283.9   379.2 1272.61
   439.1 1259.89   547.8 1258.15   606.7 1253.84   616.5  1252.5  622.64 1254.16
   626.3 1255.17   636.1  1266.6   645.9 1281.88   655.7  1287.3   774.3 1324.82
   794.1 1329.33   823.8 1340.21   873.3 1360.79   903.1 1370.96     913 1372.19
   952.6 1385.76    1012 1410.48  1031.8 1416.53  1041.8 1417.47  1081.4 1428.93
#Mann= 3 , 0 , 0
       0      .1       0   606.7    .045       0  622.64      .1       0
Bank Sta=606.7,622.64
XS Rating Curve= 0 ,0
Exp/Cntr=0.3,0.1

Type RM Length L Ch R = 1 ,756.4   ,579.3,572.1,564.8
XS GIS Cut Line= 4
     1840057.912      366143.154     1839873.017        366234.3
     1839625.621      366382.738     1839195.933      366637.946
#Sta/Elev= 30
       0    1361    68.7 1346.45    98.2 1338.46   137.4    1324   176.7 1306.22
   186.5 1300.79   196.3 1297.16   245.9 1289.05   265.8 1283.92   285.7 1282.49
   325.5 1271.24   345.4  1264.3   385.2 1243.06   395.2 1240.21   402.8 1239.44
   405.1 1239.21   417.8 1240.04   464.8 1244.78   484.7 1248.13   534.6 1249.76
   574.6 1255.98   684.6 1263.08   714.6  1271.2   784.5 1297.06   844.5 1312.76
   884.5 1324.37   904.5 1327.43   934.4 1340.32   964.4 1349.86   994.4 1357.38
#Mann= 3 , 0 , 0
       0      .1       0   402.8    .045       0   417.8      .1       0
Bank Sta=402.8,417.8
XS Rating Curve= 0 ,0
Exp/Cntr=0.3,0.1

Type RM Length L Ch R = 1 ,184.3   ,195,184.3,173.7
XS GIS Cut Line= 4
     1839906.871      365622.321     1839573.537      365713.467
     1839419.892      365893.154     1839154.267      366429.613
#Sta/Elev= 30
       0 1300.85    19.8 1299.93      79 1291.74   108.6 1286.79   148.1 1276.16
   197.5 1271.46   256.7 1261.94   296.2  1257.2   325.8 1255.94     385 1250.62
   424.4 1242.23   463.8 1231.68   473.6 1230.39   483.5 1230.92   532.7 1235.28
   542.6 1235.41   572.1 1231.46   631.9 1234.95   691.7 1235.56   761.6 1241.01
   901.2  1242.4   941.2  1244.5   971.1 1255.04     991 1258.22    1021 1269.42
  1060.9 1286.59  1080.8 1293.16  1100.8 1298.23  1170.6 1309.93  1180.6 1312.79
#Mann= 3 , 0 , 0
       0      .1       0   463.8    .045       0   483.5      .1       0
#XS Ineff= 2 , 0
                           532.3         1235.17
Permanent Ineff=
       F       F
Bank Sta=463.8,483.5
XS Rating Curve= 0 ,0
Exp/Cntr=0.3,0.1

Chan Stop Cuts=-1
Use User Specified Reach Order=0
Composite Channel Slope=5